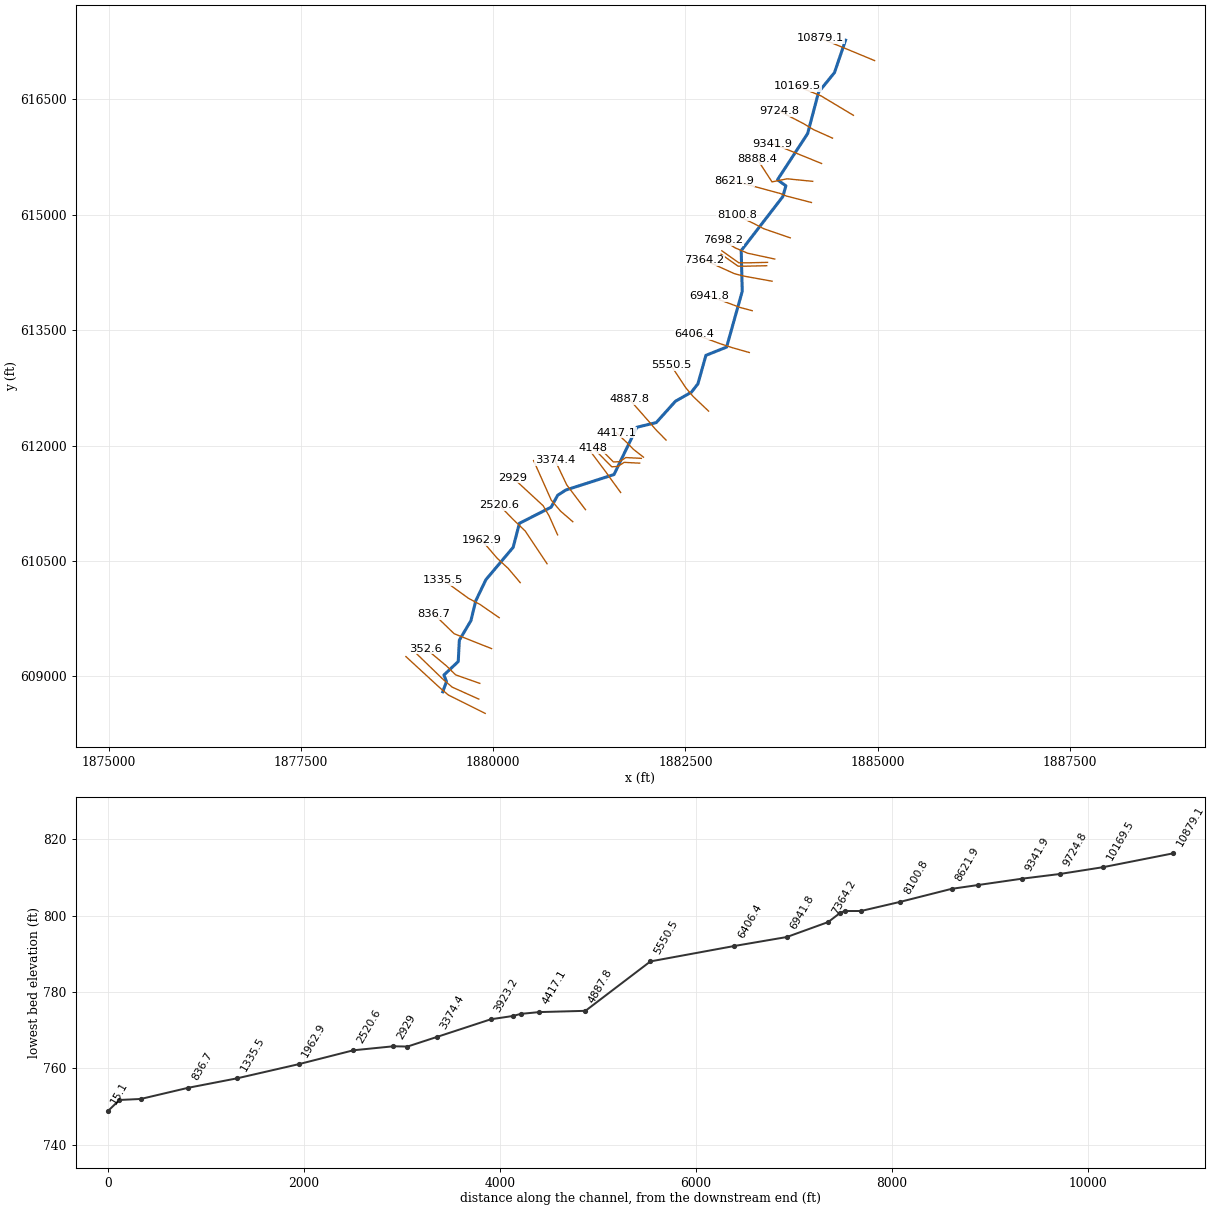
--- LaurelRun.prj (project) ---

Proj Title=LaurelRun
Current Plan=p01
Default Exp/Contr=0,0
English Units
Geom File=g01
Flow File=f01
Plan File=p01
BEGIN DESCRIPTION:
AMEC Environment & Infrastructure, 2013
Projection: NAD 1983 State Plane West Virginia South FIPS 4702 (US Feet)
Vertical Datum: NAVD 1988
END DESCRIPTION:
DSS Export Rating Curves= 0
DSS Export Rating Curve Sorted= 0
DSS Export Volume Flow Curves= 0
DXF OffsetX= 0
DXF OffsetY= 0
DXF ScaleX= 0
DXF ScaleY= 0

--- LaurelRun.p01 (plan) ---

Plan Title=Floodplain
Program Version=4.00
Geom File=g01
Flow File=f01
K Sum by GR=0
Std Step Tol=0.01
Critical Tol=0.01
Num of Std Step Trials=20
Max Error Tol=0.3
Flow Tol Ratio=0.001
Split Flow NTrial=30
Split Flow Tol=0.02
Split Flow Ratio=0.02
Log Output Level=0
Friction Slope Method=1
Unsteady Friction Slope Method=2
Unsteady Bridges Friction Slope Method=1
Global Log Level=0
CheckData=False
Run HTab=0
Run UNet=0
Run PostProcess=0
UNET Theta=0
UNET Theta Warmup=0
UNET ZTol=0
UNET ZSATol=0
UNET MxIter=0
UNET MaxInSteps=0
UNET DtIC=0
UNET DtMin=0
UNET MaxCRTS=0
UNET WFStab=0
UNET SFStab=0
UNET WFX=0
UNET SFX=0
UNET DSS MLevel=0
UNET DZMax Abort=0
UNET Convert EG Bridges=0
UNET Use Existing IB Tables=0
UNET Froude Limit=0
UNET Froude Power=0
Write IC File=0
Echo Input=False
Echo Output=False
Write Detailed=0

--- LaurelRun.f01 (steady flow) ---

Flow Title=NFF Regression Equation
Program Version=4.10
Number of Profiles= 1
Profile Names=P100yr
River Rch & RM=LaurelRun,Main            ,10879.1
 897.651
River Rch & RM=LaurelRun,Main            ,9341.9
941.8351
River Rch & RM=LaurelRun,Main            ,8100.8
1041.258
River Rch & RM=LaurelRun,Main            ,5550.5
1109.536
River Rch & RM=LaurelRun,Main            ,3072.6
1170.601
River Rch & RM=LaurelRun,Main            ,2929
1323.168
River Rch & RM=LaurelRun,Main            ,352.6
1369.712
River Rch & RM=LaurelRun,Main            ,134
1372.141
Boundary for River Rch & Prof#=LaurelRun,Main            , 1
Up Type= 0
Dn Type= 3
Dn Slope=0.00605
DSS Import GetInterval= 0
DSS Import GetPeak= 0
DSS Import FillOption= 0

--- LaurelRun.g01 (geometry) ---

Geom Title=USGS 3m DEM
Program Version=4.10

River Reach=LaurelRun       ,Main
Reach XY= 30
     1884583.131      617270.085     1884438.998      616848.055
     1884232.336      616594.484     1884089.943      616056.093
     1883697.463       615455.17      1883806.88      615377.021
     1883766.941      615236.345     1883225.612      614534.986
      1883239.15      614005.467     1883035.848      613280.762
     1882766.659      613173.075     1882662.453      612803.112
     1882577.357      612693.695     1882370.691      612577.327
     1882120.612      612299.442     1881868.789      612238.647
     1881570.965      611623.956     1880943.144      611422.353
     1880837.731      611354.356     1880753.848      611200.045
     1880340.515      610989.886     1880259.377      610677.918
     1879904.624      610256.972     1879772.643      609982.565
      1879710.13      609725.527     1879559.044      609470.223
     1879545.176       609194.12     1879358.543      609017.769
     1879392.511      608933.869     1879343.537      608800.801

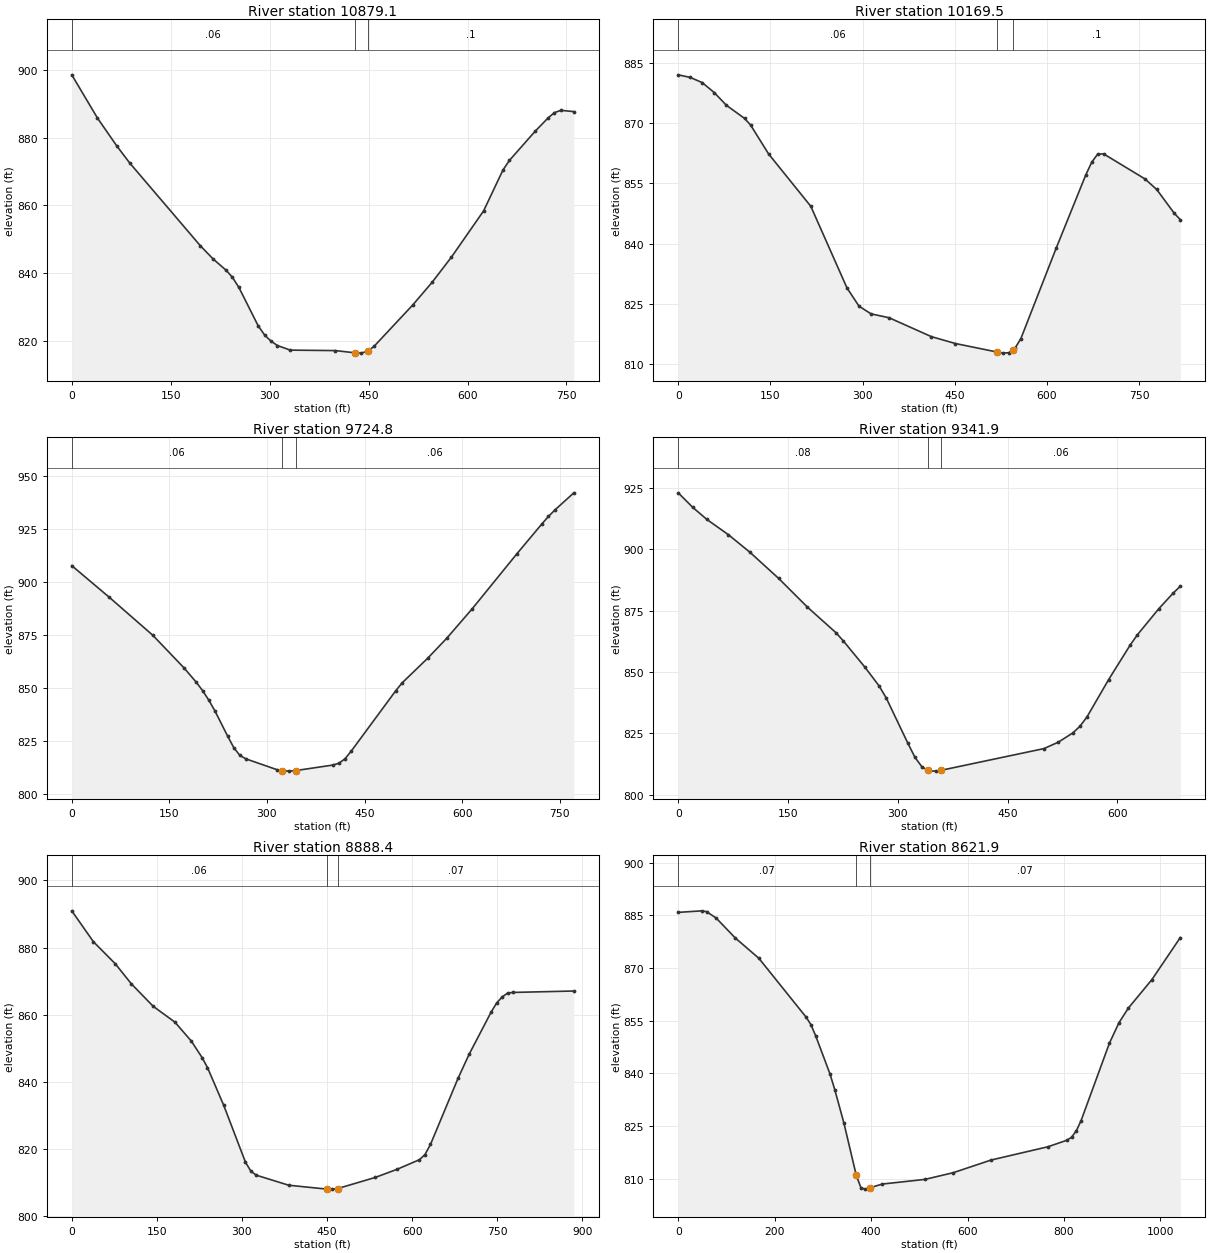
Type RM Length L Ch R = 1 ,10879.1 ,709.3,709.5,709.2
XS GIS Cut Line= 3
     1884961.054      617004.107     1884601.008        617153.5
     1884257.099      617293.611
#Sta/Elev= 30
       0  898.63      39  885.83    68.2  877.61    87.7  872.59   194.9  848.08
   214.4  844.14   233.9  840.85   243.6  838.73   253.4  835.73   282.6   824.4
   292.4  821.66   302.1  819.85   311.8  818.56   331.3   817.2   399.6  817.06
   428.9  816.42   438.7  816.31   448.7   816.9   458.2   818.3   516.8  830.52
   546.2  837.23   575.5  844.68   624.4  858.39   653.7  870.46   663.4  873.29
   702.5  881.93   722.1  885.87   731.8  887.45   741.6  888.13   761.2  887.75
#Mann= 3 , 0 , 0
       0     .06       0   428.9    .045       0   448.7      .1       0
Bank Sta=428.9,448.7
XS Rating Curve= 0 ,0
Exp/Cntr=0.3,0.1

Type RM Length L Ch R = 1 ,10169.5 ,447.9,444.8,441.1
XS GIS Cut Line= 3
     1884685.013      616293.169     1884264.509      616545.351
      1883961.96      616668.611
#Sta/Elev= 30
       0  882.03    19.6  881.38    39.2  880.08    58.8  877.58    78.4  874.44
   107.9  871.18   117.7  869.53   147.1  862.31   215.7  849.29   274.6  828.95
   294.2   824.4   313.8  822.49   343.2  821.52   411.9  816.82   451.1   815.1
   519.2  812.97   528.8  812.71   538.4  812.83     544  813.47     548  813.92
   557.6  816.35   615.2  838.93   663.3  857.14   672.9  860.28   682.5  862.27
   692.1  862.35   759.4  856.11   778.6  853.47   807.4   847.5     817  845.96
#Mann= 3 , 0 , 0
       0     .06       0   519.2    .045       0     544      .1       0
Bank Sta=519.2,544
XS Rating Curve= 0 ,0
Exp/Cntr=0.3,0.1

Type RM Length L Ch R = 1 ,9724.8  ,379.1,382.9,386.6
XS GIS Cut Line= 4
     1884413.485      615996.555     1884168.693       616105.93
     1884038.485      616184.055     1883725.985      616345.513
#Sta/Elev= 30
       0   907.7    57.4  892.87   124.5  874.92   172.4  859.58   191.5  852.74
   201.1  848.82   210.7  844.31   220.2  839.18   239.4   827.5     249  821.98
   258.5  818.28   268.1  816.64   315.6  811.57   322.8  811.13   334.6  810.91
     344  811.16     401  813.76   410.5   814.6     420  816.73   429.7   820.4
   498.1  848.84   507.9  852.52     547  864.07   576.3  873.49   615.4  887.35
   683.8  913.16   722.9  927.48   732.6  930.85   742.4  933.88   771.7     942
#Mann= 3 , 0 , 0
       0     .06       0   322.8    .045       0     344     .06       0
Bank Sta=322.8,344
XS Rating Curve= 0 ,0
Exp/Cntr=0.3,0.1

Type RM Length L Ch R = 1 ,9341.9  ,440.1,453.5,466.1
XS GIS Cut Line= 2
     1884270.767      615666.772     1883635.571      615925.556
#Sta/Elev= 30
       0  922.88    19.6  917.03    39.2  912.04    68.6  905.84      98   898.7
   137.2  888.07   176.4  876.42   215.6  865.96   225.4   862.7   254.8  852.05
   274.4  844.35   284.2  839.42   313.6   821.1   323.4  815.29   333.2  811.33
  340.61  810.18   342.9  809.79   352.7  809.69   358.7     810   499.7  818.86
   519.3  821.48   538.9   825.2   548.7  827.89   558.5  831.78   587.9  846.88
   617.3  860.91   627.1  865.08   656.5  875.74   676.1  882.08   685.9  884.91
#Mann= 3 , 0 , 0
       0     .08       0  340.61    .045       0   358.7     .06       0
Bank Sta=340.61,358.7
XS Rating Curve= 0 ,0
Exp/Cntr=0.3,0.1

Type RM Length L Ch R = 1 ,8888.4  ,279.5,266.5,253.1
XS GIS Cut Line= 4
     1884155.788      615434.821     1883822.455      615467.808
     1883626.274      615427.877     1883435.302       615721.28
#Sta/Elev= 30
       0  890.96    38.3  881.72    76.6   875.2   105.3  869.15   143.6   862.5
   181.8  857.79   210.6  852.18   229.7  847.24   239.3  844.24     268  832.95
   306.2  816.05   315.8  813.35   325.4  812.16   382.6  809.17   449.4  808.02
   458.9  808.01   468.8  808.18   535.2   811.5   574.1  813.96     613  816.79
   622.7  818.31   632.4  821.32     681  841.03   700.5  848.18   739.4  860.79
   749.1   863.5   758.8  865.29   768.6  866.46   778.3  866.64   885.2  867.06
#Mann= 3 , 0 , 0
       0     .06       0   449.4    .045       0   468.8     .07       0
Bank Sta=449.4,468.8
XS Rating Curve= 0 ,0
Exp/Cntr=0.3,0.1

Type RM Length L Ch R = 1 ,8621.9  ,522.3,521,517.9
XS GIS Cut Line= 4
      1884139.44      615159.923     1883815.582       615243.55
     1883733.192      615277.116     1883136.836      615438.569
#Sta/Elev= 30
       0  885.83    49.2  886.27      59  886.02    78.7  884.21     118  878.58
   167.2  872.76   265.6  855.93   275.4   853.8   285.3   850.6   314.8   839.8
   324.6  835.37   343.4  825.95   369.2  810.98     379  807.39   387.9  807.02
   396.8  807.38   423.4  808.47   511.7  809.79   570.6  811.71     649  815.31
   766.7  819.08   805.9  820.93   815.7   821.8   825.5  823.59   835.3  826.46
   894.2  848.55   913.8  854.34   933.4  858.55   982.4  866.69  1041.3  878.66
#Mann= 3 , 0 , 0
       0     .07       0   369.2    .045       0   396.8     .07       0
Bank Sta=369.2,396.8
XS Rating Curve= 0 ,0
Exp/Cntr=0.3,0.1

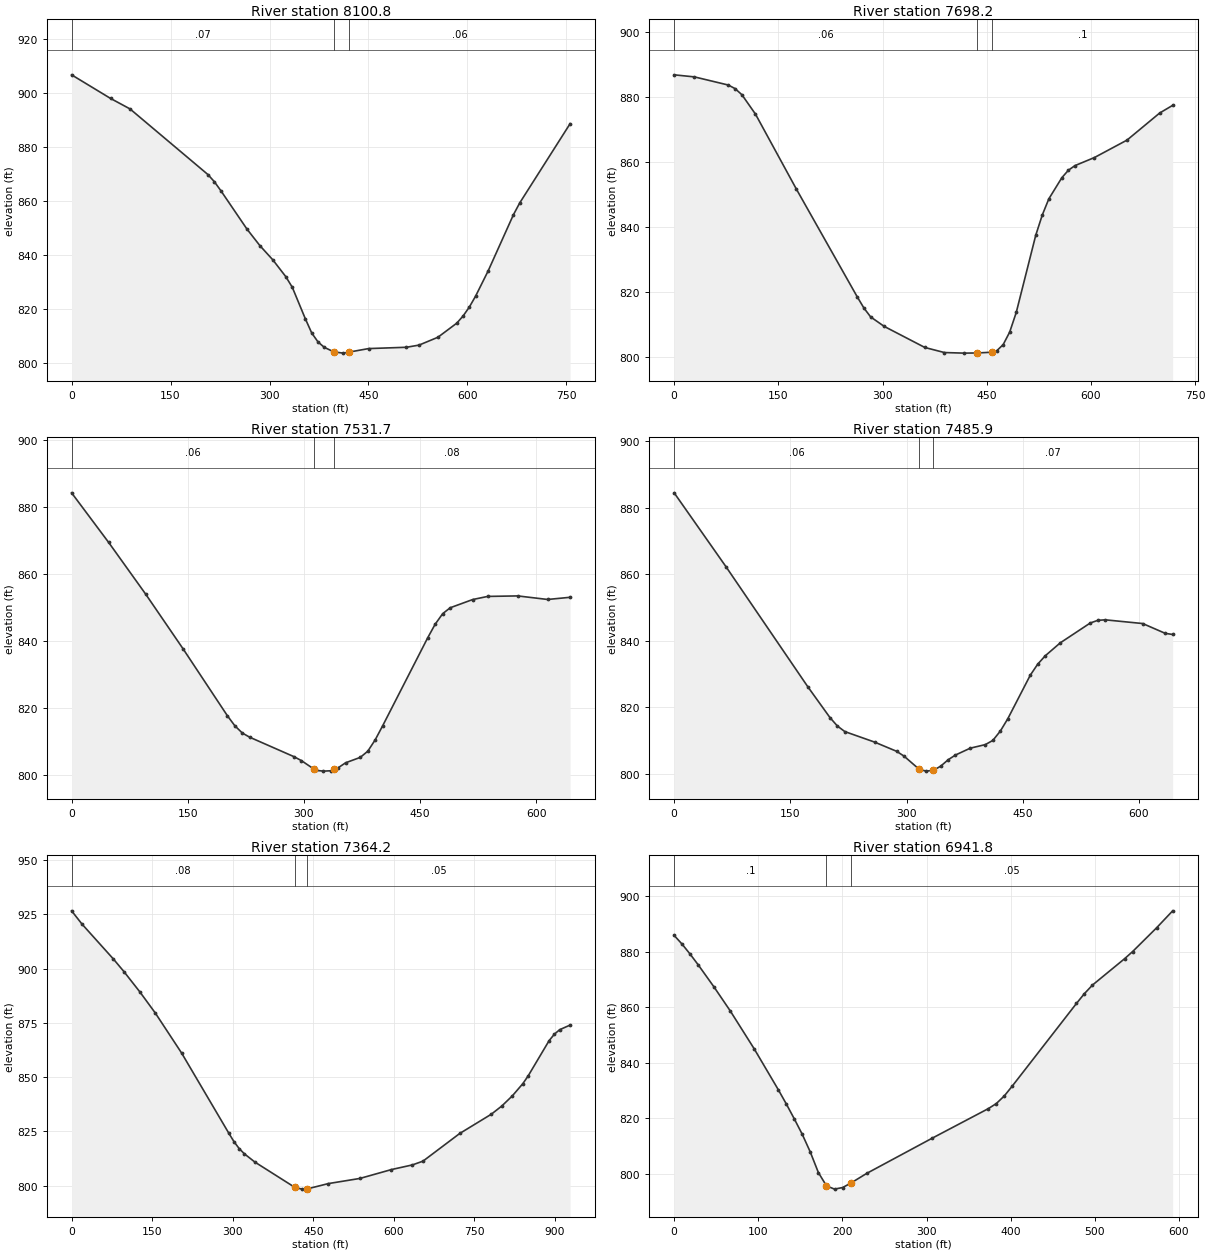
Type RM Length L Ch R = 1 ,8100.8  ,400.6,402.6,404.2
XS GIS Cut Line= 4
     1883863.832      614700.287     1883519.648      614818.777
     1883392.478      614885.183      1883168.52      614991.954
#Sta/Elev= 30
       0  906.65      59  897.92    88.5  894.04   206.6  869.74   216.4  867.08
   226.3  863.74   265.6  849.62   285.3  843.45     305  838.16   324.7  831.93
   334.5  828.01   354.2  816.39     364  811.07   373.6  807.74   383.1  805.76
  397.74  804.07   411.8  803.63   420.1  803.99   450.1  805.31   507.5   805.8
   526.6   806.6   555.2   809.5   583.8  814.72   593.4  817.38   602.9   820.7
   612.4  824.75   631.5  834.13   669.7  854.87   679.2  859.22   755.6  888.57
#Mann= 3 , 0 , 0
       0     .07       0  397.74    .045       0   420.1     .06       0
Bank Sta=397.74,420.1
XS Rating Curve= 0 ,0
Exp/Cntr=0.3,0.1

Type RM Length L Ch R = 1 ,7698.2  ,157.3,166.5,175.9
XS GIS Cut Line= 4
     1883661.575      614425.114     1883308.711      614501.069
     1883144.648      614571.381     1882994.908      614668.169
#Sta/Elev= 30
       0  886.76    29.3  886.12      78  883.62    87.8  882.51    97.6  880.63
   117.1  874.68   175.6  851.78   263.4  818.59   273.2  815.08   282.9  812.35
   302.4  809.44     361  802.95   389.1   801.4   417.3  801.22   436.1  801.27
   457.9   801.5   464.3  801.92   473.7  803.84   483.1  807.71   492.5  813.71
   520.6  837.46     530  843.68   539.4  848.63   558.2  855.15   567.6  857.44
     577  858.85   605.1  861.34     652   866.7     699  875.02   717.7  877.38
#Mann= 3 , 0 , 0
       0     .06       0   436.1    .045       0   457.9      .1       0
Bank Sta=436.1,457.9
XS Rating Curve= 0 ,0
Exp/Cntr=0.3,0.1

Type RM Length L Ch R = 1 ,7531.7  ,45.5,45.8,45.9
XS GIS Cut Line= 4
     1883567.825      614381.711     1883309.145      614375.852
     1883195.212      614375.852     1882973.858      614532.102
#Sta/Elev= 30
       0  884.17    47.9  869.37    95.8  853.92   143.8  837.71   201.2   817.7
   210.8  814.72   220.4  812.57     230  811.31   287.2  805.51   296.7  804.34
   312.5  801.88   315.7  801.44   325.2  801.21   334.7  801.32  339.07  801.72
   344.2  802.21   353.7  803.69   372.7  805.31   382.4  807.15     392  810.55
   401.7  814.77   459.8  840.98   469.4  845.01   479.1  848.15   488.8  849.91
   517.8  852.36   537.2  853.29   575.9  853.44   614.6  852.38   643.6  853.03
#Mann= 3 , 0 , 0
       0     .06       0   312.5    .045       0  339.07     .08       0
Bank Sta=312.5,339.07
XS Rating Curve= 0 ,0
Exp/Cntr=0.3,0.1

Type RM Length L Ch R = 1 ,7485.9  ,127.8,121.7,115.7
XS GIS Cut Line= 4
     1883557.408      614338.308     1883298.728      614332.449
     1883184.796      614332.449     1882963.441      614488.699
#Sta/Elev= 30
       0  884.51    67.1  862.21   172.5  826.15   201.2  816.84   210.8   814.3
   220.4  812.63   258.8  809.47   287.2   806.7   296.7  805.26   316.3   801.3
   325.2  800.73   334.7  800.97   344.2  802.24   353.7  804.14   363.2  805.58
   382.4  807.65   401.7  808.71   411.4  809.97   421.1  812.78   430.7  816.48
   459.8  829.62   469.4  832.94   479.1  835.45   498.5  839.35   537.2  845.32
   546.9  846.12   556.5  846.28   604.9  845.16     634  842.21   643.6  841.87
#Mann= 3 , 0 , 0
       0     .06       0   316.3    .045       0   334.7     .07       0
Bank Sta=316.3,334.7
XS Rating Curve= 0 ,0
Exp/Cntr=0.3,0.1

Type RM Length L Ch R = 1 ,7364.2  ,424.4,422.4,420
XS GIS Cut Line= 4
     1883626.853      614136.919      1883262.27      614202.891
     1883139.006      614234.141     1882746.645      614411.225
#Sta/Elev= 30
       0  926.61    19.5  920.46      78  904.35    97.5  898.58   126.8  889.34
     156  879.45   204.8  861.07   292.5  824.19   302.2  820.26     312  817.02
   321.8  814.58   341.2  810.81   415.9  799.09   429.2  798.33     439  798.46
   478.1  800.89   536.8  803.26   595.5  807.35   634.6   809.5   654.2  811.23
   722.7     824   781.4  832.86     801  836.66   820.5  841.31   840.1  846.95
   849.9  850.48     889  866.77   898.8  869.75   908.6  871.81   928.1  873.95
#Mann= 3 , 0 , 0
       0     .08       0   415.9    .045       0     439     .05       0
Bank Sta=415.9,439
XS Rating Curve= 0 ,0
Exp/Cntr=0.3,0.1

Type RM Length L Ch R = 1 ,6941.8  ,534.5,535.4,535.9
XS GIS Cut Line= 4
     1883368.606      613753.673     1883212.356      613795.339
     1883058.711      613852.631     1882808.276      613944.732
#Sta/Elev= 30
       0  885.87     9.5   882.7      19  879.12    28.5   875.3    47.6  867.19
    66.6  858.69    95.1     845   123.7  830.29   133.2  825.16   142.7  819.79
   152.2   814.2   161.7  807.86   171.4  800.39     181   795.6   190.6   794.4
   200.3  794.98   209.9  796.56   229.2  800.13   306.4  812.72   373.3   823.4
   382.9  825.25   392.4     828   401.9  831.57   478.2  861.36   487.7  864.91
   497.2  867.97   535.3  877.45   544.9  880.04   573.5  888.64   592.5  894.73
#Mann= 3 , 0 , 0
       0      .1       0     181    .045       0   209.9     .05       0
Bank Sta=181,209.9
XS Rating Curve= 0 ,0
Exp/Cntr=0.3,0.1

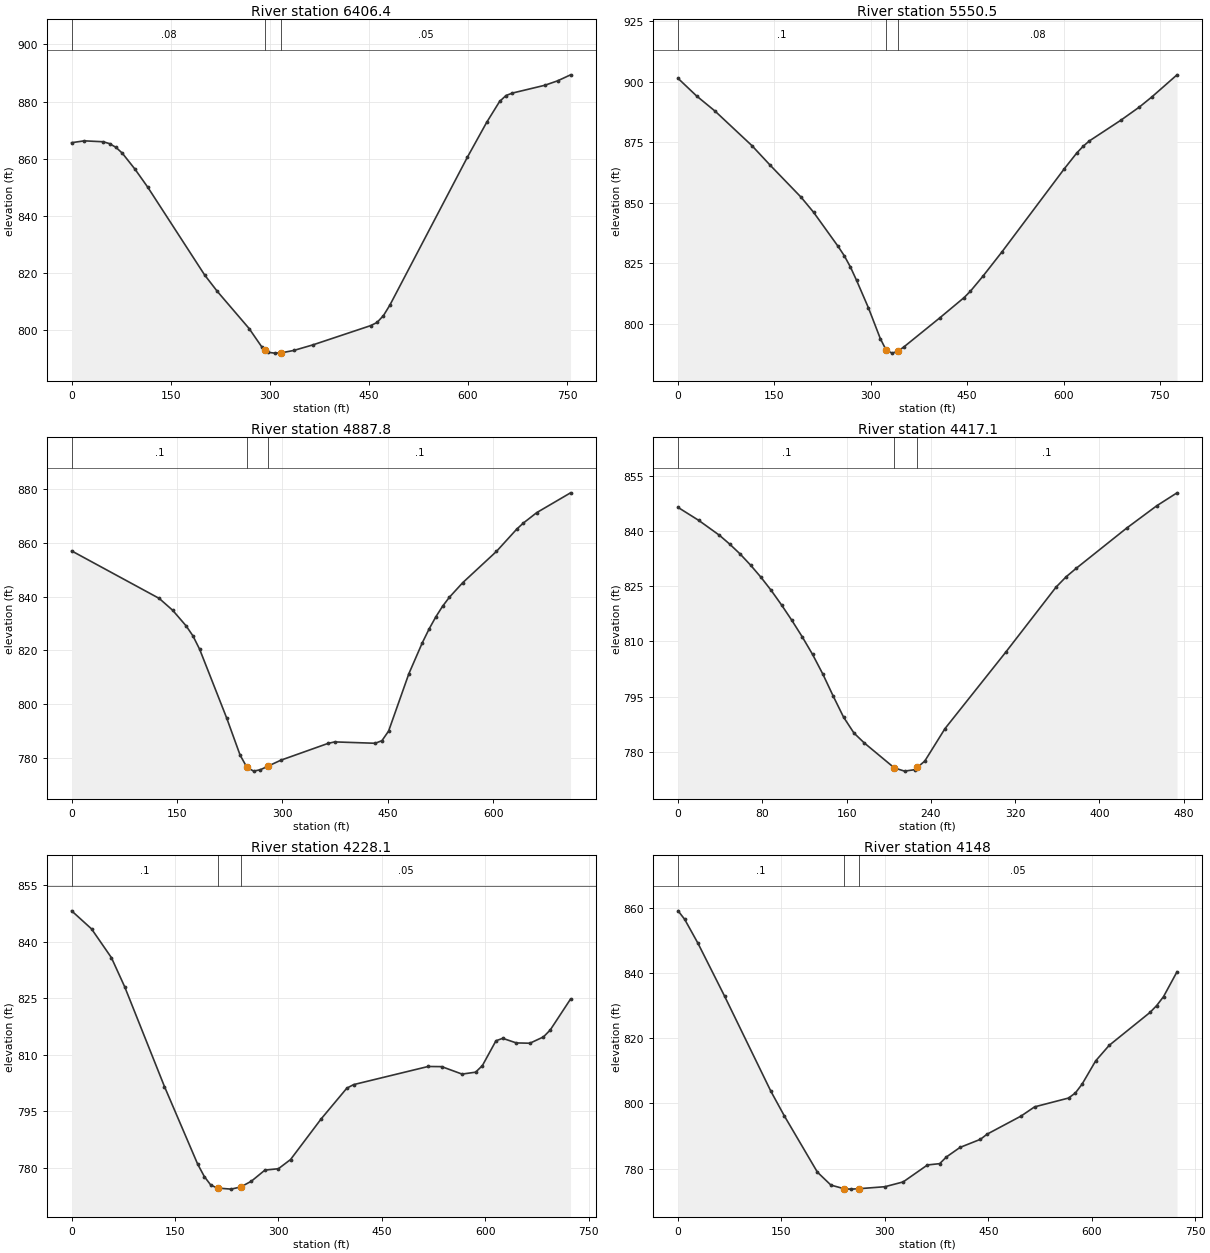
Type RM Length L Ch R = 1 ,6406.4  ,868.3,855.9,843.1
XS GIS Cut Line= 4
      1883331.28      613209.923     1883109.926      613272.857
     1882944.995       613327.11     1882615.134      613448.638
#Sta/Elev= 30
       0  865.62    19.2  866.26    47.9  865.94    57.5  865.28    67.1  863.99
    76.7  861.96    95.9  856.37   115.1  850.11   201.4  819.36   220.5  813.65
   268.7  800.65     288  794.19   293.2  793.19   297.6  792.34   307.3  792.05
   316.9  792.13   336.2  792.98   365.2  794.93   452.6  801.66   462.3  802.76
   472.1  805.18   481.9  808.89     599  860.49   628.3  872.72   647.9  880.03
   657.6  882.11   667.4  882.97   716.2  885.68   735.8  887.25   755.3  889.34
#Mann= 3 , 0 , 0
       0     .08       0   293.2    .045       0   316.9     .05       0
Bank Sta=293.2,316.9
XS Rating Curve= 0 ,0
Exp/Cntr=0.3,0.1

Type RM Length L Ch R = 1 ,5550.5  ,662.2,662.7,663.1
XS GIS Cut Line= 4
     1882801.766      612448.204     1882599.943      612639.176
     1882504.457      612752.023     1882311.315      613044.992
#Sta/Elev= 30
       0  901.37    28.7  894.15    57.5  887.88     115  873.61   143.7  865.45
   191.6   852.3   210.8  846.17   249.1  832.04   258.7  828.19   268.3  823.52
   277.8  818.04   296.3  806.69   314.8  793.99     324  789.19   333.3  788.01
   342.5  788.85   351.8  790.64   407.2  802.53   445.2  810.93   454.9  813.52
   474.4  819.72   503.7  829.64   601.1  864.06   620.6   870.6   630.4  873.33
   640.1  875.56   688.9  884.06   718.1  889.57   737.6  893.76   776.6  902.84
#Mann= 3 , 0 , 0
       0      .1       0     324    .045       0   342.5     .08       0
Bank Sta=324,342.5
XS Rating Curve= 0 ,0
Exp/Cntr=0.3,0.1

Type RM Length L Ch R = 1 ,4887.8  ,469.1,470.7,471.6
XS GIS Cut Line= 4
     1882248.091      612072.336     1882113.543      612209.055
     1882013.716      612326.242     1881772.831       612599.68
#Sta/Elev= 30
       0  857.11   124.7   839.4   143.9  834.97     163  829.17   172.6  825.49
   182.2  820.48   220.7  794.86   239.9  780.98   249.6  776.44   259.2  775.06
   268.8  775.59   280.1  776.98   297.7  779.12   364.9  785.38   374.5  785.95
   432.1  785.44   441.7   786.4   451.2  789.98     480  811.33   499.2  822.89
   508.8     828   518.4  832.52     528  836.47   537.6   839.8   556.7  845.26
   604.7  856.91   633.4  865.16     643  867.48   662.2  871.39   710.2  878.74
#Mann= 3 , 0 , 0
       0      .1       0   249.6    .045       0   280.1      .1       0
Bank Sta=249.6,280.1
XS Rating Curve= 0 ,0
Exp/Cntr=0.3,0.1

Type RM Length L Ch R = 1 ,4417.1  ,147.9,189,236.4
XS GIS Cut Line= 4
     1881954.399      611850.078     1881822.889      611952.942
     1881742.449      612035.444     1881602.837      612166.484
#Sta/Elev= 30
       0  846.44    19.6  842.92    39.3  838.86    49.1  836.44    58.9  833.78
    68.8  830.76    78.6  827.48    88.4  823.88    98.2  819.93     108  815.74
   117.9  811.24   127.7  806.46   137.5  801.08   147.3  795.12   157.1  789.42
     167  785.08   176.6  782.44   205.4  775.59     215  774.73   224.6  775.12
   227.1  775.73   234.2  777.46   253.4  786.29   310.9  807.01   358.8  824.75
   368.4  827.57   377.9  829.86   425.8   840.8   454.5   846.9   473.7  850.41
#Mann= 3 , 0 , 0
       0      .1       0   205.4    .045       0   227.1      .1       0
Bank Sta=205.4,227.1
XS Rating Curve= 0 ,0
Exp/Cntr=0.3,0.1

Type RM Length L Ch R = 1 ,4228.1  ,75.8,80.1,83.4
XS GIS Cut Line= 5
     1881927.055      611834.453     1881725.232      611844.869
     1881643.201      611791.484     1881563.774      611787.578
     1881321.587      612032.369
#Sta/Elev= 30
       0  848.19    28.9  843.39    57.7  835.76      77  828.01   134.7  801.51
   182.8  780.93   192.5  777.61   202.1  775.29   211.9  774.54   231.4  774.26
   245.3  774.83   260.8  776.37   280.4  779.31     300  779.68   317.6  782.12
   361.8  792.87   399.2  801.07     409  802.02   517.2  806.84   536.9   806.8
   566.4  804.82   586.1  805.33   595.9  807.08   615.6  813.67   625.4  814.32
   645.1   813.1   664.8  813.02   684.5   814.7   694.3  816.53   723.8  824.76
#Mann= 3 , 0 , 0
       0      .1       0   211.9    .045       0   245.3     .05       0
Bank Sta=211.9,245.3
XS Rating Curve= 0 ,0
Exp/Cntr=0.3,0.1

Type RM Length L Ch R = 1 ,4148    ,273.5,224.8,170.9
XS GIS Cut Line= 5
      1881904.92      611771.953     1881703.097      611782.369
     1881621.066      611728.984     1881541.639      611725.078
     1881299.451      611969.869
#Sta/Elev= 30
       0  859.12     9.6   856.5    28.9  849.14    67.4  832.96   134.7  803.71
     154  796.24   202.1  778.92   221.7  774.95   241.2  773.81     251  773.71
   261.9  773.83     300  774.45   326.5  775.92   361.8  781.13   379.5  781.53
   389.3  783.59     409  786.51   438.5  788.99   448.4  790.59   497.6  796.14
   517.2  798.96   566.4  801.66   576.3  803.21   586.1  805.94   605.8  813.08
   625.4  817.84   684.5  827.92   694.3  830.05   704.2  832.78   723.8  840.42
#Mann= 3 , 0 , 0
       0      .1       0   241.2    .045       0   261.9     .05       0
Bank Sta=241.2,261.9
XS Rating Curve= 0 ,0
Exp/Cntr=0.3,0.1

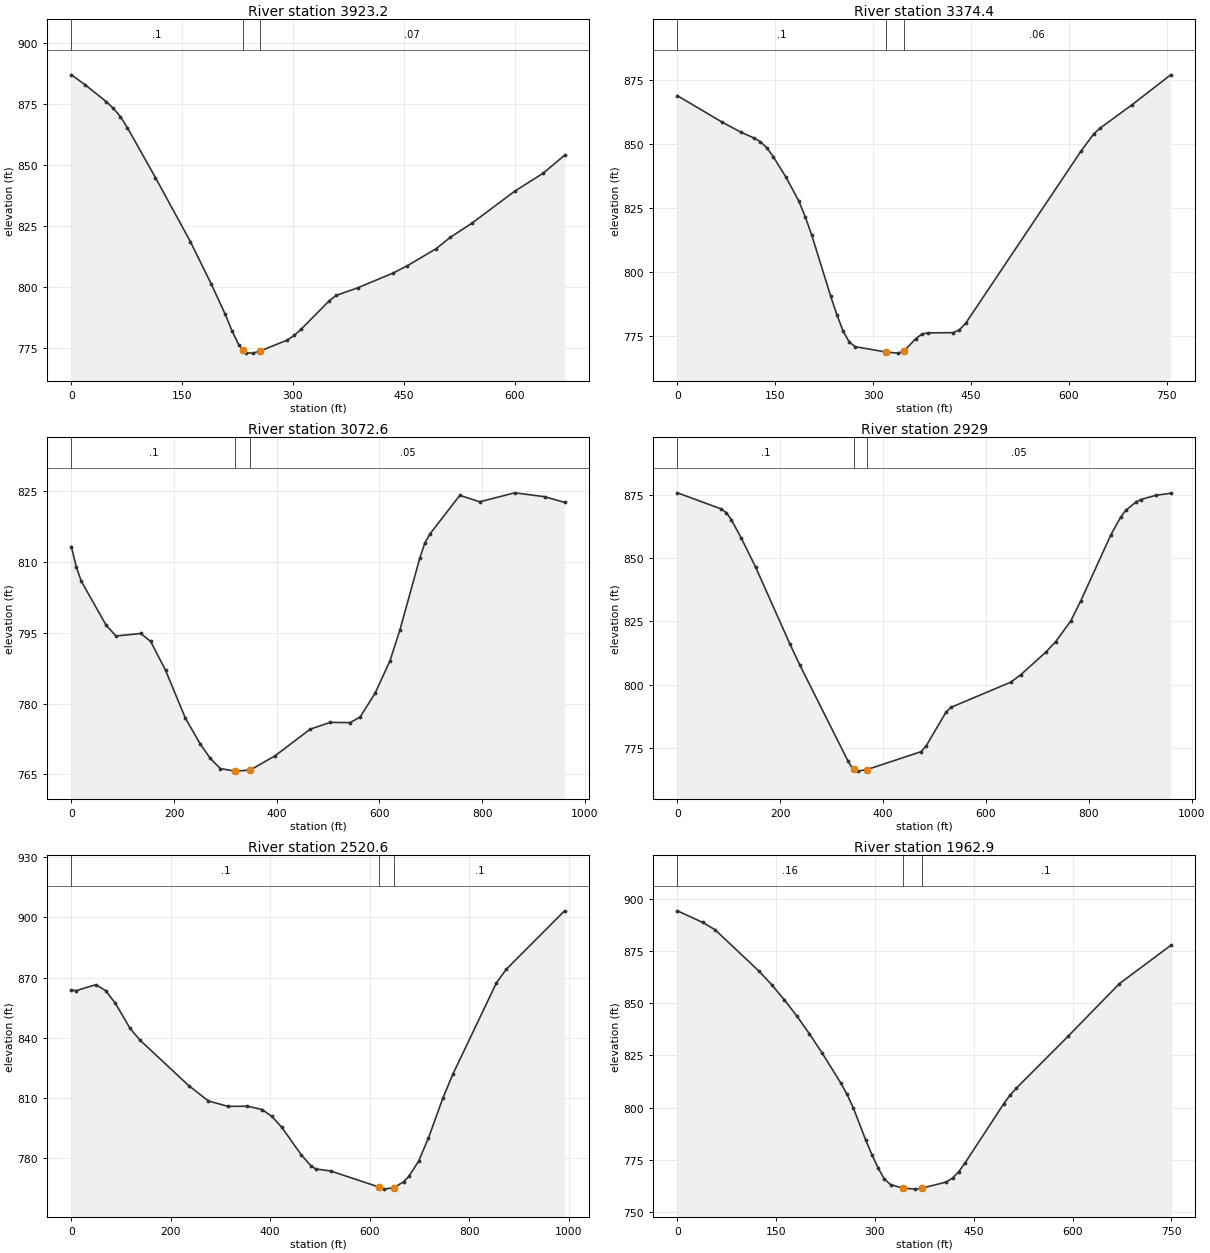
Type RM Length L Ch R = 1 ,3923.2  ,546.3,548.7,549.1
XS GIS Cut Line= 4
     1881657.814      611390.912     1881551.477      611536.312
     1881464.671      611657.839     1881261.691      611928.203
#Sta/Elev= 30
       0  886.87      19  882.72    47.4  875.86    56.9  873.12    66.4  869.76
    75.8  865.26   113.8   844.8   161.2   818.5   189.5  801.11   208.1   788.9
   217.5  781.99   226.8  776.13   232.2  774.28   236.1  772.94   245.5  772.85
   254.8  773.62   292.1  778.18   301.5  780.08   310.8  782.57   348.8  794.21
   358.5  796.49   387.4  799.58   435.7  805.68     455  808.69   493.7  815.63
     513   820.3     542  826.03   599.9  839.14   638.6  846.55   667.6  853.91
#Mann= 3 , 0 , 0
       0      .1       0   232.2    .045       0   254.8     .07       0
Bank Sta=232.2,254.8
XS Rating Curve= 0 ,0
Exp/Cntr=0.3,0.1

Type RM Length L Ch R = 1 ,3374.4  ,302,301.9,302.3
XS GIS Cut Line= 4
     1881199.914      611167.388     1881052.345        611362.7
     1880956.859      611488.569     1880804.949      611807.579
#Sta/Elev= 30
       0  868.97    68.5  858.64    97.9  854.61   117.5  852.43   127.3  850.93
   137.1  848.57   146.9   845.1   166.5  837.04     186  827.78   195.8  821.63
   205.6  814.65     235  790.43   244.8  782.97   254.1  776.76   263.4  772.57
   272.7  770.74   319.1  768.69   337.7  768.23     347  768.98   365.6  773.94
   374.9  775.71   384.2  776.15   422.4  776.24   432.2  777.32     442  779.98
   618.7  847.31   638.3  854.08   648.2  856.34   697.2  865.49   756.1  877.15
#Mann= 3 , 0 , 0
       0      .1       0   319.1    .045       0     347     .06       0
Bank Sta=319.1,347
XS Rating Curve= 0 ,0
Exp/Cntr=0.3,0.1

Type RM Length L Ch R = 1 ,3072.6  ,147.1,143.6,140.6
XS GIS Cut Line= 4
     1881034.984      611011.138     1880874.393      611150.027
     1880755.036      611291.086     1880525.001      611805.409
#Sta/Elev= 30
       0  813.18     9.6  808.95    19.3  805.89    67.6  796.61    86.9  794.28
   135.1  794.82   154.4  793.15   183.4  787.06     222  776.93   251.2  771.41
   270.7  768.39   290.1  766.24   319.3   765.7   348.5  765.93   397.1  768.97
   465.1  774.57     504  776.01   542.8  775.96   562.2  777.12   591.4  782.15
   620.5  789.03     640  795.62   678.8  810.83   688.5  813.98   698.2  815.85
   756.5  824.04   795.4  822.67   863.4  824.57   921.7  823.75   960.5  822.55
#Mann= 3 , 0 , 0
       0      .1       0   319.3    .045       0   348.5     .05       0
Bank Sta=319.3,348.5
XS Rating Curve= 0 ,0
Exp/Cntr=0.3,0.1

Type RM Length L Ch R = 1 ,2929    ,402,408.4,414.3
XS GIS Cut Line= 4
     1880837.501      610839.697     1880724.654      611091.433
     1880648.699      611219.471     1880255.904      611581.885
#Sta/Elev= 30
       0  875.88    85.6  869.46    95.1  868.03   104.6  865.32   123.7  858.15
   152.2  846.42   218.8  816.03   237.8  807.83   331.7  769.75     341  766.66
   342.8  766.49   350.3  765.77   368.9  766.41   473.3  773.43     483  775.52
   521.9  788.97   531.6  790.98   648.2  800.96   667.7  803.92   716.3  812.83
   735.7  817.04   764.8  825.16   784.3  833.12   842.6  859.14     862  866.28
   871.7  868.92   891.2  872.16   900.9  873.23     930  874.87   959.2  875.72
#Mann= 3 , 0 , 0
       0      .1       0   342.8    .045       0   368.9     .05       0
Bank Sta=342.8,368.9
XS Rating Curve= 0 ,0
Exp/Cntr=0.3,0.1

Type RM Length L Ch R = 1 ,2520.6  ,557.3,557.7,557.7
XS GIS Cut Line= 4
     1880700.782      610464.263     1880416.494       610889.61
     1880260.244       611039.35     1880075.782      611228.152
#Sta/Elev= 30
       0  863.74     9.8  863.46    49.2  866.43    68.9   863.5    88.6  857.19
   118.1  844.71   137.7  838.94   236.1  816.23   275.5  808.62   314.8  805.89
   354.2  805.98   383.7  804.33   403.4  800.86   423.1  795.54   462.4   781.8
   482.1  776.27   491.9  774.74   521.4  773.75   619.8  765.67   629.6  764.72
   649.3   765.5     669  768.51   678.8  771.09   698.5  778.62   718.2  790.14
   747.6  810.18   767.1  821.79   855.1  867.41   874.7  874.06     992  903.17
#Mann= 3 , 0 , 0
       0      .1       0   619.8    .045       0   649.3      .1       0
Bank Sta=619.8,649.3
XS Rating Curve= 0 ,0
Exp/Cntr=0.3,0.1

Type RM Length L Ch R = 1 ,1962.9  ,621.3,627.3,633.1
XS GIS Cut Line= 4
      1880351.39      610219.037      1880197.31      610401.329
     1880051.911      610535.878     1879847.918      610772.423
#Sta/Elev= 30
       0  894.12    38.2   888.6    57.3  885.04   124.1  865.22   143.2  858.78
   162.3   851.6   181.4  843.81   200.5   835.3   219.6  826.23   248.1   811.8
   257.6  806.39     267  800.02   285.8  784.68   295.3  777.58   304.7  771.23
   314.2  765.93   323.6  763.26   342.4  761.55   361.3  761.08   370.8  761.51
   408.5   764.5   417.9   766.4   427.4  769.49   436.8   773.6   495.4  801.81
   505.1  805.99   514.9  809.41     593  834.07     671  859.24   749.1  877.58
#Mann= 3 , 0 , 0
       0     .16       0   342.4    .045       0   370.8      .1       0
Bank Sta=342.4,370.8
XS Rating Curve= 0 ,0
Exp/Cntr=0.3,0.1

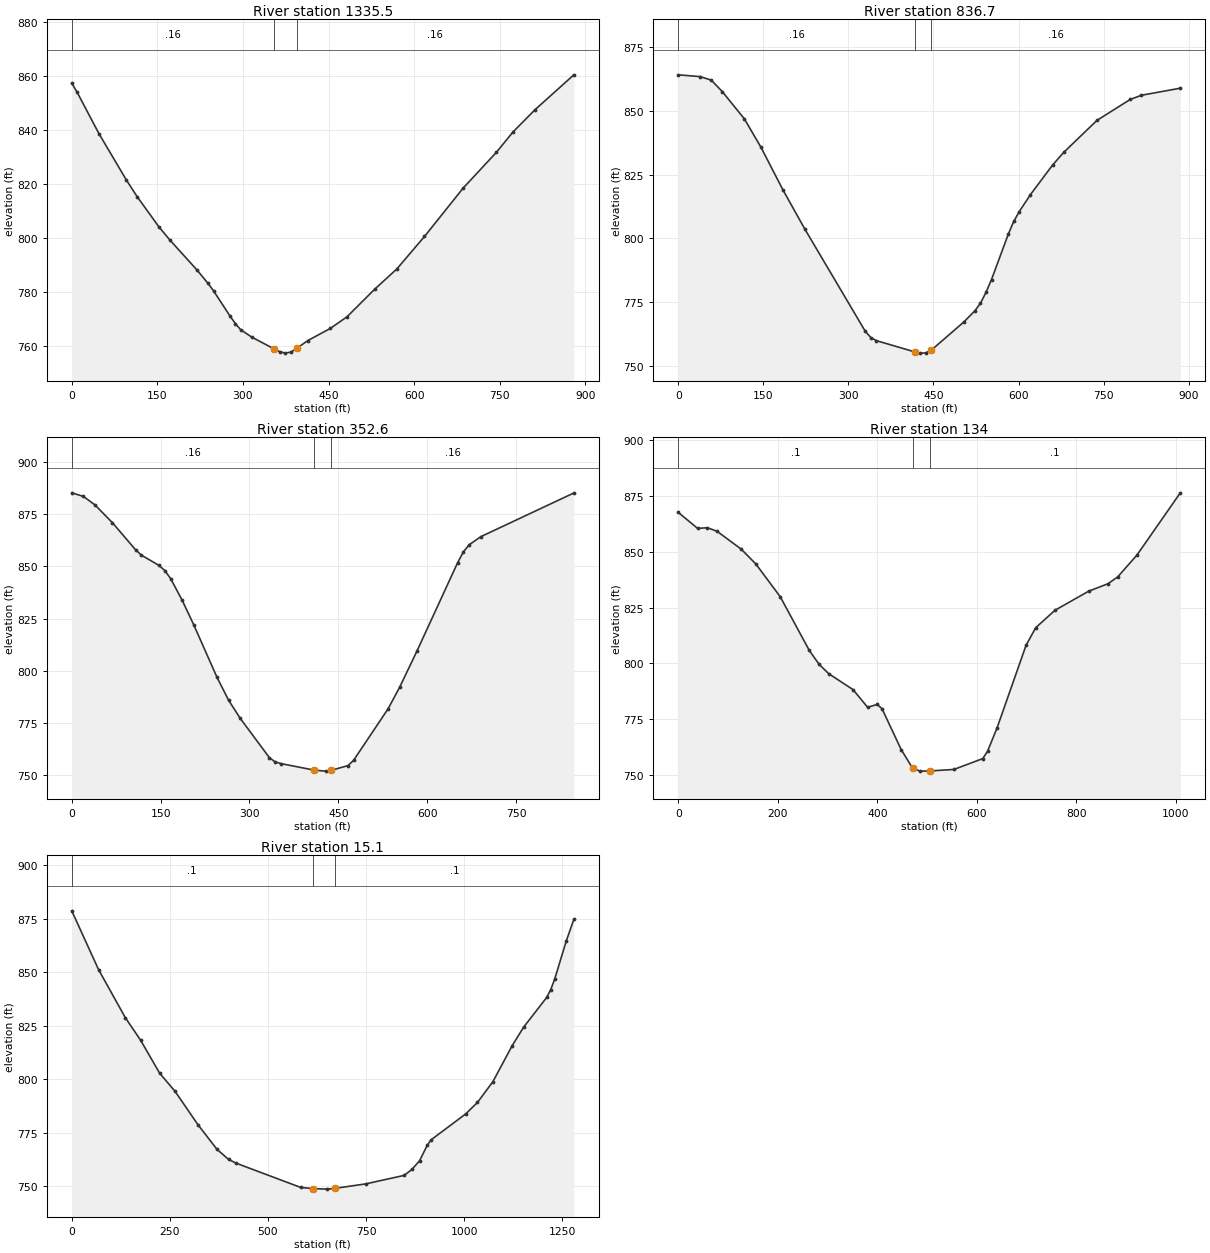
Type RM Length L Ch R = 1 ,1335.5  ,496.2,498.8,501
XS GIS Cut Line= 4
     1880077.952      609763.308     1879826.216      609936.919
     1879678.647      610015.044     1879348.786       610253.76
#Sta/Elev= 30
       0  857.38     9.6  853.91    47.8   838.6    95.6  821.53   114.7   815.3
   152.9  804.09     172  799.26   219.8   788.1   238.9  783.17   248.5  780.45
   277.1   771.2   286.7  768.33   296.2  766.02   315.6   763.3   354.9  758.92
   364.7  757.88   374.6  757.38   384.4   757.8   394.2  759.13   413.8  762.04
   453.1  766.52   482.5  770.85   530.9  781.05   569.7  788.54   618.2  800.58
     686   818.5   744.2  831.74   773.3  839.27   812.1  847.56     880  860.45
#Mann= 3 , 0 , 0
       0     .16       0   354.9    .045       0   394.2     .16       0
Bank Sta=354.9,394.2
XS Rating Curve= 0 ,0
Exp/Cntr=0.3,0.1

Type RM Length L Ch R = 1 ,836.7   ,493.3,484.1,474.8
XS GIS Cut Line= 4
     1879978.126      609361.832     1879698.178       609472.51
     1879492.015      609554.975     1879231.598      609806.711
#Sta/Elev= 30
       0  864.13    38.8  863.43    58.3  862.04    77.7  857.54   116.5  846.87
   145.7  835.77   184.5  819.02   223.4  803.52     330   763.4   339.6  761.02
   349.3  759.81   416.9  755.39   426.5   754.9   436.2  754.97   445.8  755.98
   503.8  767.17   523.1  771.52   532.9  774.49   542.6  778.71   552.4  783.79
   581.8  801.47   591.6  806.61   601.4  810.48     621   817.1   660.1  828.73
   679.7  833.69   738.4  846.27   797.2  854.49   816.8  856.11   885.3  858.89
#Mann= 3 , 0 , 0
       0     .16       0   416.9    .045       0   445.8     .16       0
Bank Sta=416.9,445.8
XS Rating Curve= 0 ,0
Exp/Cntr=0.3,0.1

Type RM Length L Ch R = 1 ,352.6   ,217.4,218.6,212.6
XS GIS Cut Line= 4
     1879825.457      608909.756     1879510.787      609020.433
     1879395.769      609133.281     1879124.502      609358.975
#Sta/Elev= 30
       0  885.22    19.6   883.5    39.2  879.43    68.7  870.89   107.9  857.89
   117.7  855.35   147.2  850.48     157  848.02   166.8  844.19   186.4  833.77
     206  821.97   245.3  796.82   264.9  785.84   284.5   777.2   333.6  758.43
     343  756.45   352.5  755.61   409.4  752.44   428.4  751.97   437.8  752.34
   466.3  754.62   475.7  757.13   533.9  781.76   553.5  792.12   582.9  809.56
   651.5  851.83   661.3  857.02   671.1  860.39   690.7  864.25   847.6  885.15
#Mann= 3 , 0 , 0
       0     .16       0   409.4    .045       0   437.8     .16       0
Bank Sta=409.4,437.8
XS Rating Curve= 0 ,0
Exp/Cntr=0.3,0.1

Type RM Length L Ch R = 1 ,134     ,118.5,118.9,126.5
XS GIS Cut Line= 4
     1879812.436       608705.04     1879465.539      608861.398
     1879348.352      608961.225     1879007.314      609290.977
#Sta/Elev= 30
       0  867.74      39  860.55    58.5  860.86      78  859.26   126.8   851.2
   156.1  844.55   204.9  829.92   263.4   805.8   282.9  799.63   302.4  795.38
   351.2  788.26   380.5  780.34   399.8   781.6   409.4  779.71   447.9  761.38
   471.1  752.94   486.1   751.7   505.6  751.78   553.8  752.45   611.9  757.32
   621.6  760.67   640.9  771.25     699  808.21   718.4  816.06   757.1  823.85
   824.9  832.42   863.6  835.74     883  838.81   921.7  848.59  1008.8   876.5
#Mann= 3 , 0 , 0
       0      .1       0   471.1    .045       0   505.6      .1       0
Bank Sta=471.1,505.6
XS Rating Curve= 0 ,0
Exp/Cntr=0.3,0.1

Type RM Length L Ch R = 1 ,15.1    ,10.9,15.1,19.4
XS GIS Cut Line= 4
     1879895.661      608519.819      1879416.06      608758.534
     1879298.873       608858.36     1878864.845      609257.666
#Sta/Elev= 30
       0  878.64    68.2  851.23   136.4   828.8   175.3  818.28     224  802.84
     263  794.45   321.4  778.85   370.1  767.31   399.4  762.65   418.8  760.86
   583.8  749.51   613.6  749.02   651.2  748.75   670.4  749.11   748.6  751.18
   846.9  755.16   866.6  757.92   886.3  761.99   905.9  769.24   915.8   771.8
  1004.2   783.9  1033.7   789.2    1073  798.86  1122.2  815.69  1151.6  824.38
  1210.6  838.32  1220.5  841.87  1230.3   846.6  1259.8   864.4  1279.4  874.64
#Mann= 3 , 0 , 0
       0      .1       0   613.6    .045       0   670.4      .1       0
Bank Sta=613.6,670.4
XS Rating Curve= 0 ,0
Exp/Cntr=0.3,0.1

Chan Stop Cuts=-1
Use User Specified Reach Order=0
Composite Channel Slope=5